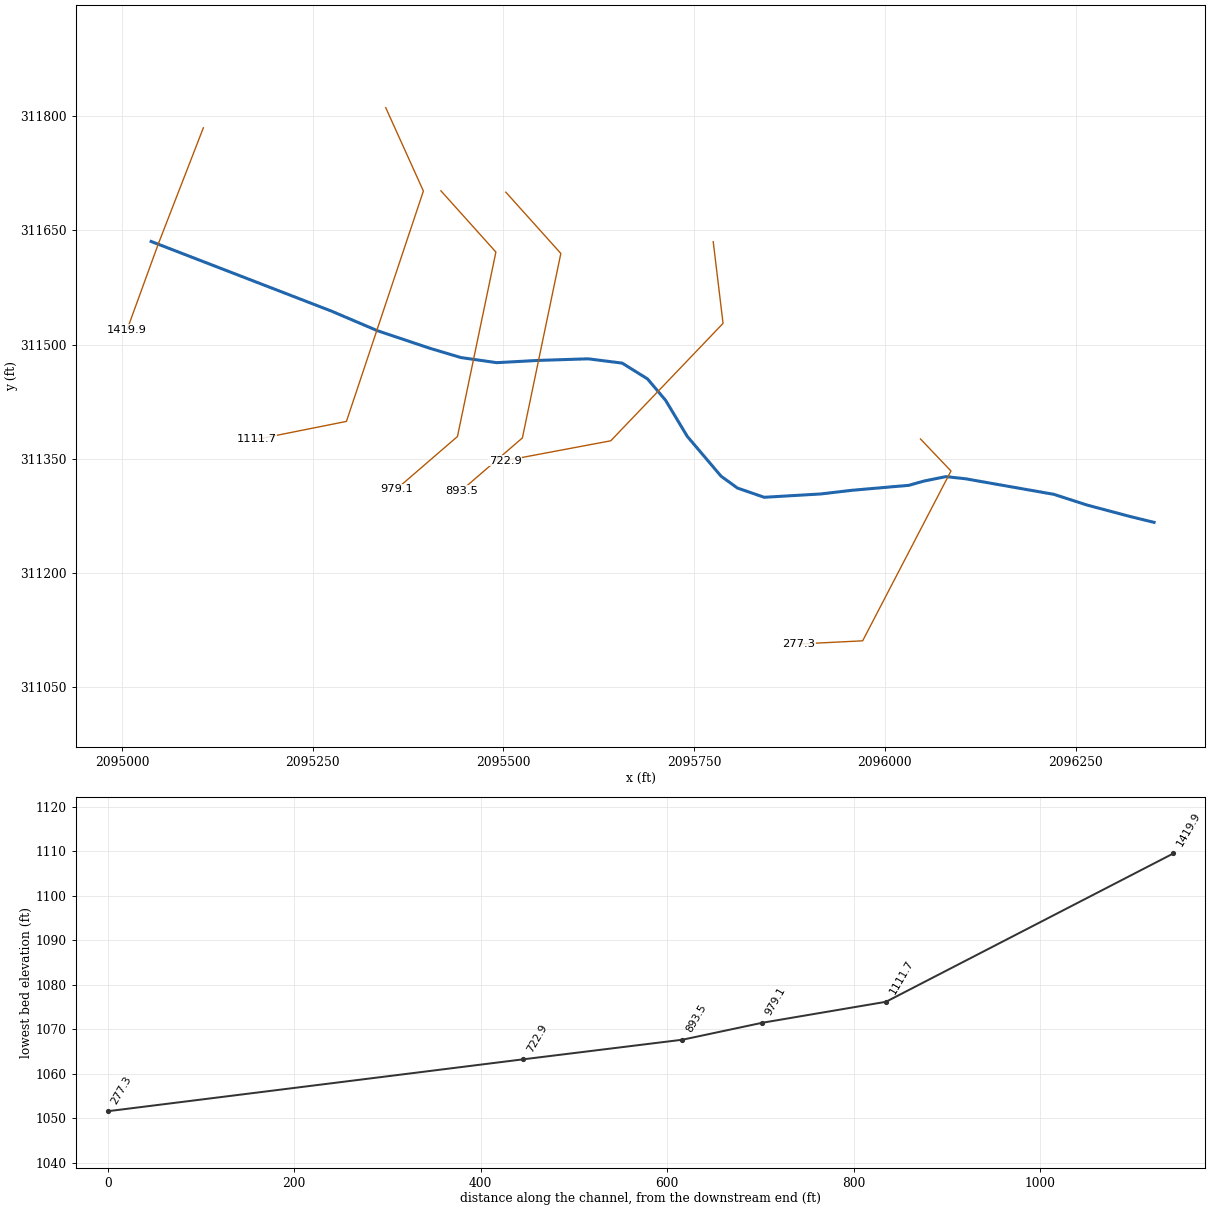
--- ASHSPRCR.prj (project) ---

Proj Title=ASHSPRCR
Current Plan=p01
Default Exp/Contr=0,0
English Units
Geom File=g01
Flow File=f01
Plan File=p01
BEGIN DESCRIPTION:
END DESCRIPTION:
DSS Export Rating Curves= 0
DSS Export Rating Curve Sorted= 0
DSS Export Volume Flow Curves= 0
DXF OffsetX= 0
DXF OffsetY= 0
DXF ScaleX= 0
DXF ScaleY= 0

--- ASHSPRCR.p01 (plan) ---

Plan Title=Floodplain
Program Version=4.00
Geom File=g01
Flow File=f01
K Sum by GR=0
Std Step Tol=0.01
Critical Tol=0.01
Num of Std Step Trials=20
Max Error Tol=0.3
Flow Tol Ratio=0.001
Split Flow NTrial=30
Split Flow Tol=0.02
Split Flow Ratio=0.02
Log Output Level=0
Friction Slope Method=1
Unsteady Friction Slope Method=2
Unsteady Bridges Friction Slope Method=1
Global Log Level=0
CheckData=False
Run HTab=0
Run UNet=0
Run PostProcess=0
UNET Theta=0
UNET Theta Warmup=0
UNET ZTol=0
UNET ZSATol=0
UNET MxIter=0
UNET MaxInSteps=0
UNET DtIC=0
UNET DtMin=0
UNET MaxCRTS=0
UNET WFStab=0
UNET SFStab=0
UNET WFX=0
UNET SFX=0
UNET DSS MLevel=0
UNET DZMax Abort=0
UNET Convert EG Bridges=0
UNET Use Existing IB Tables=0
UNET Froude Limit=0
UNET Froude Power=0
Write IC File=0
Echo Input=False
Echo Output=False
Write Detailed=0

--- ASHSPRCR.f01 (steady flow) ---

Flow Title=NFF Regression Equation
Program Version=4.00
Number of Profiles=1
Profile Names=P100yr
River Rch & RM=ASHSPRCR,Main      ,1419.9
     427
River Rch & RM=ASHSPRCR,Main      ,277.3
     432
Boundary for River Rch & Prof#=ASHSPRCR,Main      ,1
Up Type=0
Dn Type=3
Dn Slope=0.032156

--- ASHSPRCR.g01 (geometry) ---

Geom Title=USGS 10m DEM
Program Version=4.00

River Reach=ASHSPRCR        ,Main
Reach XY= 25
     2095038.263      311635.616     2095275.121      311543.926
     2095334.882      311518.396      2095404.16      311495.113
     2095444.656      311483.042     2095491.429      311476.376
     2095545.455      311479.333     2095611.146      311481.432
     2095655.781      311475.794     2095688.972      311455.078
     2095712.721      311426.865     2095741.068      311379.564
     2095785.368      311327.275     2095806.826       311311.69
     2095841.965      311299.533     2095916.131      311303.934
     2095957.395      311308.782     2096031.502       311315.26
     2096051.573      311320.917     2096080.129      311326.678
     2096105.599      311323.875      2096221.51      311303.453
     2096265.192      311289.324     2096321.632      311274.282
     2096352.959      311266.611

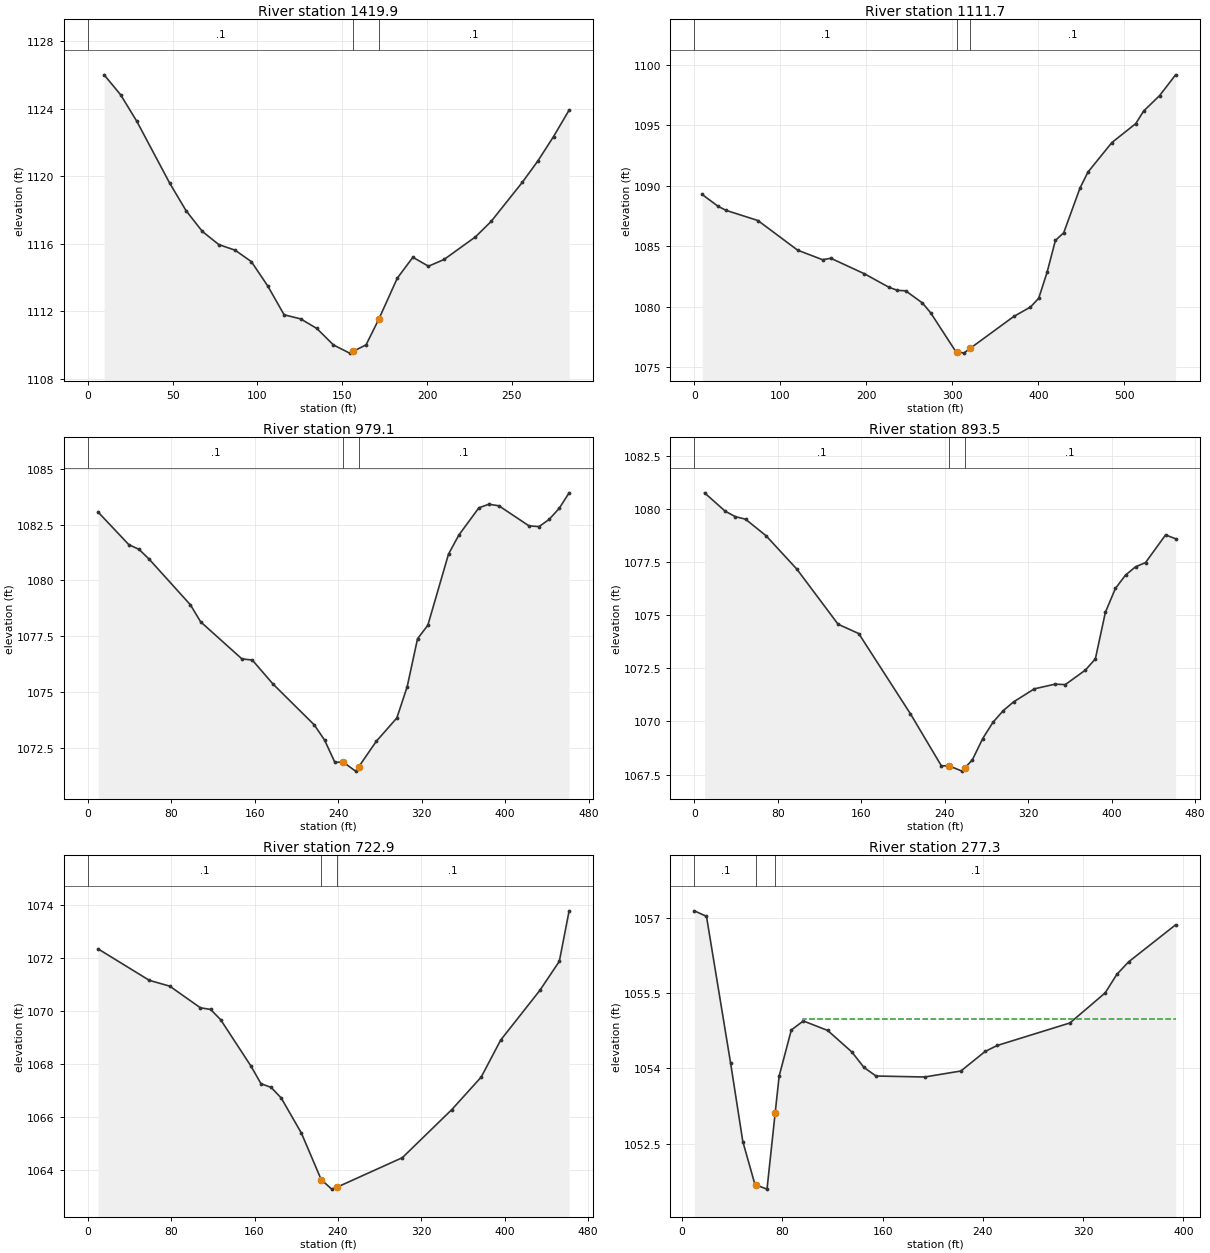
Type RM Length L Ch R = 1 ,1419.9  ,307.1,308.2,308.8
XS GIS Cut Line= 3
     2095106.777      311784.905     2095047.588      311632.006
     2095006.712      311519.413
#Sta/Elev= 28
     9.6 1126.01    19.3 1124.83    28.9 1123.25    48.2  1119.6    57.9 1117.96
    67.5 1116.73    77.2 1115.95    86.8 1115.62    96.4 1114.94   106.1 1113.49
   115.7 1111.79   125.4 1111.55     135 1110.98   144.7 1110.01   154.3 1109.52
   156.5 1109.63     164 1110.01   171.5 1111.53   182.4 1113.96   191.6  1115.2
   200.8 1114.67     210 1115.07   228.5 1116.41   237.7 1117.32   256.1 1119.64
   265.3 1120.91   274.5 1122.35   283.7 1123.92
#Mann= 3 , 0 , 0
       0      .1       0   156.5    .045       0   171.5      .1       0
Bank Sta=156.5,171.5
XS Rating Curve= 0 ,0
Exp/Cntr=0.3,0.1

Type RM Length L Ch R = 1 ,1111.7  ,129.9,132.6,135.2
XS GIS Cut Line= 4
     2095345.834      311811.315       2095395.2      311701.852
     2095294.322      311399.217     2095176.273      311375.608
#Sta/Elev= 30
     9.2 1089.29    27.7 1088.31    36.9 1087.98    73.9 1087.14   120.1 1084.69
   149.1  1083.9   158.7 1084.02   197.4 1082.75   226.4 1081.62   236.1 1081.37
   245.7 1081.33   265.1 1080.33   274.7 1079.52   303.7 1076.34   305.6 1076.31
   313.4 1076.18   320.6 1076.57   371.4 1079.21   390.8 1079.99   400.4 1080.72
   410.1 1082.86   419.8  1085.5   429.4 1086.12   448.3 1089.81   457.6 1091.14
   485.4 1093.58   513.2 1095.15   522.4 1096.19     541 1097.47   559.5 1099.18
#Mann= 3 , 0 , 0
       0      .1       0   305.6    .045       0   320.6      .1       0
Bank Sta=305.6,320.6
XS Rating Curve= 0 ,0
Exp/Cntr=0.3,0.1

Type RM Length L Ch R = 1 ,979.1   ,85.7,85.6,85.5
XS GIS Cut Line= 4
     2095418.116      311702.183     2095490.235      311621.674
      2095439.85      311379.357     2095359.868      311310.227
#Sta/Elev= 30
     9.8 1083.06    39.3  1081.6    49.1 1081.39      59 1080.94    98.3 1078.91
   108.1 1078.15   147.7 1076.49   157.6 1076.44   177.4 1075.37     217 1073.54
   226.9 1072.86   236.8 1071.86   244.6 1071.88   256.6 1071.47   259.6 1071.66
   276.4  1072.8   296.2 1073.85   306.1 1075.25     316 1077.39   325.9    1078
   345.7 1081.18   355.6 1082.03   374.8 1083.25   384.4 1083.41     394 1083.34
   422.9 1082.44   432.5 1082.41   442.1 1082.73   451.7 1083.22   461.3 1083.92
#Mann= 3 , 0 , 0
       0      .1       0   244.6    .045       0   259.6      .1       0
Bank Sta=244.6,259.6
XS Rating Curve= 0 ,0
Exp/Cntr=0.3,0.1

Type RM Length L Ch R = 1 ,893.5   ,183.2,170.6,158
XS GIS Cut Line= 4
     2095503.239      311700.358     2095575.358      311619.849
     2095524.974      311377.532     2095444.992      311308.402
#Sta/Elev= 30
     9.8 1080.75    29.5 1079.89    39.3 1079.63    49.1 1079.51    68.8 1078.73
    98.3 1077.16   137.8 1074.57   157.6 1074.13   207.1 1070.36   236.8 1067.91
   244.1 1067.91   256.6 1067.66   259.1  1067.8   266.5 1068.19   276.4 1069.19
   286.3 1069.96   296.2 1070.51   306.1 1070.92   325.9 1071.53   345.7 1071.75
   355.6 1071.73   374.8 1072.41   384.4 1072.94     394 1075.13   403.6 1076.25
   413.3 1076.88   422.9 1077.27   432.5 1077.47   451.7 1078.77   461.3 1078.59
#Mann= 3 , 0 , 0
       0      .1       0   244.1    .045       0   259.1      .1       0
Bank Sta=244.1,259.1
XS Rating Curve= 0 ,0
Exp/Cntr=0.3,0.1

Type RM Length L Ch R = 1 ,722.9   ,418.8,445.7,449.9
XS GIS Cut Line= 4
     2095775.103      311635.315     2095787.981      311527.998
     2095640.803      311373.752     2095502.517      311347.705
#Sta/Elev= 21
     9.8 1072.35      59 1071.16    78.6 1070.94   108.1 1070.12   117.8 1070.06
   127.5 1069.67   156.5 1067.92   166.2 1067.25   175.9 1067.11   185.6 1066.71
     205 1065.38     224 1063.62   234.1 1063.26     239 1063.33   301.9 1064.45
   349.4 1066.27   377.6  1067.5   396.3  1068.9   433.9 1070.78   452.6 1071.88
     462 1073.79
#Mann= 3 , 0 , 0
       0      .1       0     224    .045       0     239      .1       0
Bank Sta=224,239
XS Rating Curve= 0 ,0
Exp/Cntr=0.3,0.1

Type RM Length L Ch R = 1 ,277.3   ,292.3,277.3,284.9
XS GIS Cut Line= 4
      2096046.74      311376.173     2096086.726      311334.082
     2095970.978      311111.005     2095886.798      311106.796
#Sta/Elev= 24
     9.7 1057.15    19.4 1057.04    38.7  1054.1    48.4 1052.54    58.1 1051.68
    59.2 1051.67    67.7 1051.59    74.2 1053.11    77.4 1053.85    87.1 1054.77
    96.7 1054.95   116.1 1054.76   135.4 1054.33   145.1 1054.02   154.7 1053.85
   193.4 1053.83   222.4 1053.95   241.7 1054.34   251.4 1054.46   309.4 1054.91
   337.5 1055.51   346.8 1055.88   356.2 1056.13   393.7 1056.87
#Mann= 3 , 0 , 0
     9.7      .1       0    59.2    .045       0    74.2      .1       0
#XS Ineff= 2 , 0
                           96.72         1054.99
Permanent Ineff=
       F       F
Bank Sta=59.2,74.2
XS Rating Curve= 0 ,0
Exp/Cntr=0.3,0.1

Chan Stop Cuts=-1
Use User Specified Reach Order=0